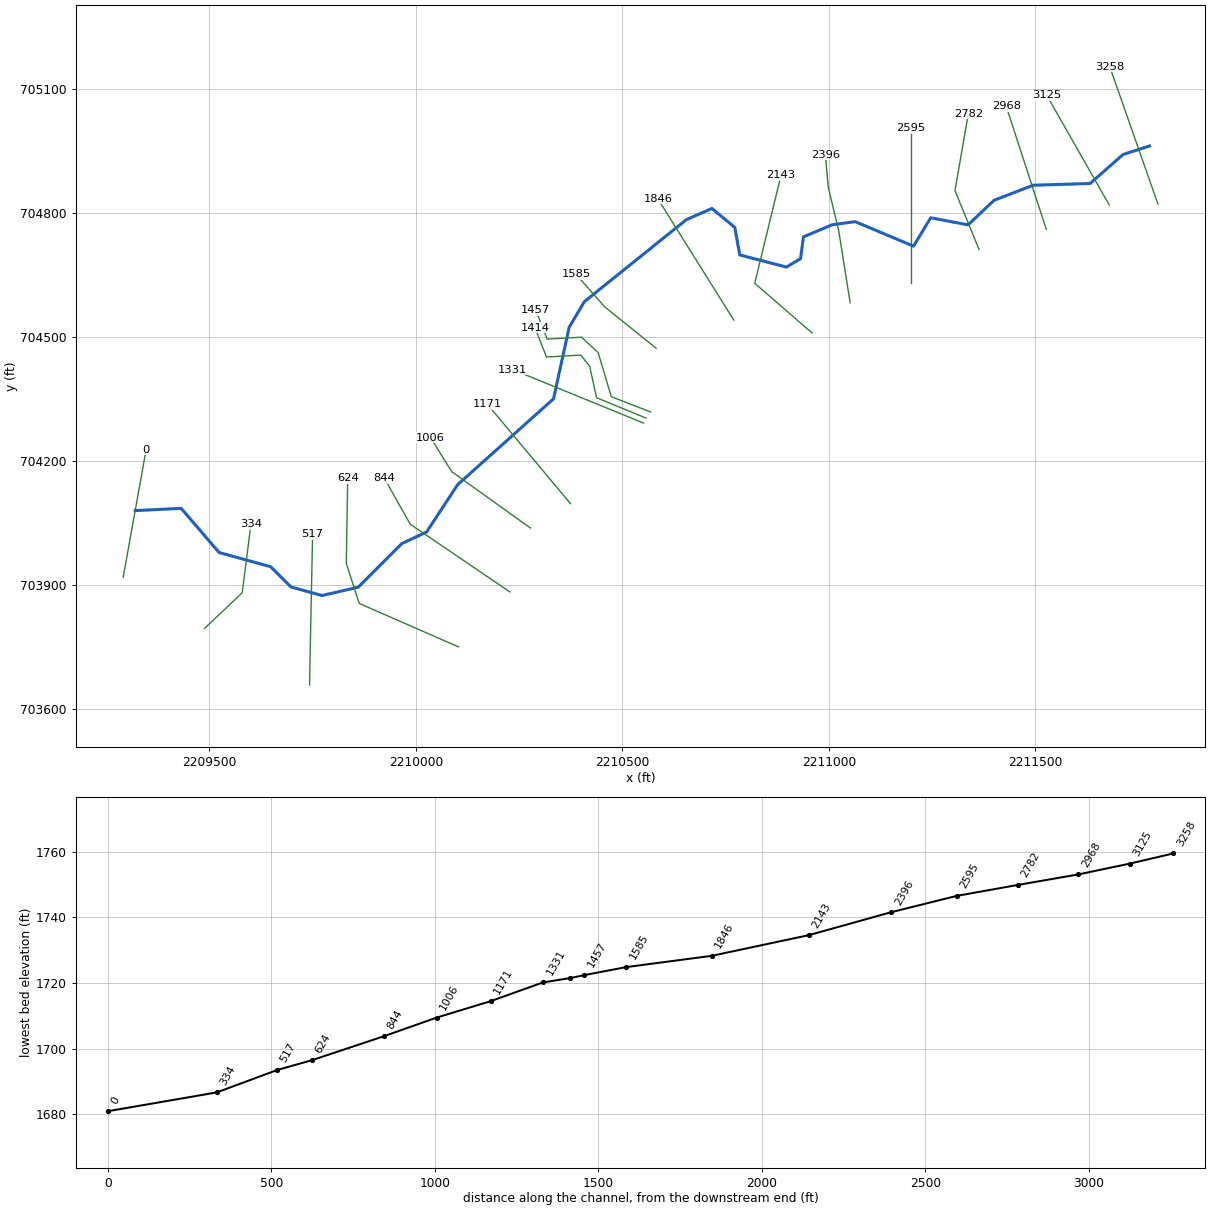
--- SANDRNT1A.prj (project) ---

Proj Title=SANDRNT1A
Current Plan=p01
Default Exp/Contr=0,0
English Units
Geom File=g01
Flow File=f01
Plan File=p01
BEGIN DESCRIPTION:
---------- MODELED AS PART OF WVEMD CTP PROGRAM, 2023----------
Stream Name: Sand Run Tributary 1a
Flood Zone:  AFH
Upshur County, WV
HEC-RAS Version: RAS 6.3
Vertical Datum: NAVD88
Projection: NAD 1983 StatePlane West Virginia S FIPS 4702 (US Feet)
Terrain: 1-meter LIDAR (FEMA Region III 3DEP collected 2016-2018)
Land Use: 2019 NLCD
Hydrologic Method:
WV 2010 Regional Regression Equations
Additional Model Notes:
Coincident peak with SANDRNT1; KWSEL tie-in used
END DESCRIPTION:
DSS Export Rating Curves= 0
DSS Export Rating Curve Sorted= 0
DSS Export Volume Flow Curves= 0
DXF OffsetX= 0
DXF OffsetY= 0
DXF ScaleX= 0
DXF ScaleY= 0

--- SANDRNT1A.p01 (plan) ---

Plan Title=Floodplain
Program Version=6.31
Short Identifier=Floodplain
Geom File=g01
Flow File=f01
Subcritical Flow
K Sum by GR= 0
Std Step Tol= 0.01
Critical Tol= 0.01
Num of Std Step Trials= 20
Max Error Tol= 0.3
Flow Tol Ratio= 0.001
Split Flow NTrial= 30
Split Flow Tol= 0.02
Split Flow Ratio= 0.02
Log Output Level= 0
Friction Slope Method= 1
Unsteady Friction Slope Method= 2
Unsteady Bridges Friction Slope Method= 1
Parabolic Critical Depth
Global Vel Dist= 0 , 0 , 0
Global Log Level= 0
CheckData=True
Encroach Param=-1 ,0,0, 0
Mapping Interval=1HOUR
Computation Time Step Use Courant=        0
Computation Time Step Use Time Series=    0
Computation Time Step Count To Double=0
Computation Time Step Max Doubling=0
Computation Time Step Max Halving=0
Computation Time Step Residence Courant=0
Run HTab= 0
Run UNet= 0
Run Sediment= 0
Run PostProcess= 0
Run WQNet= 0
Run RASMapper=-1
UNET Theta= 0
UNET Theta Warmup= 0
UNET ZTol= 0
UNET ZSATol= 0
UNET MxIter= 0
UNET Max Iter WO Improvement= 0
UNET MaxInSteps= 0
UNET DtIC= 0
UNET DtMin= 0
UNET MaxCRTS= 0
UNET WFStab= 0
UNET SFStab= 0
UNET WFX= 1
UNET SFX= 1
UNET Gravity=32.17405
UNET 1D Methodology=Finite Difference
UNET DSS MLevel= 1
UNET Pardiso=0
UNET DZMax Abort= 0
UNET Use Existing IB Tables= 0
UNET Froude Reduction=False
UNET Froude Limit= 0
UNET Froude Power= 0
UNET D1 Cores= 0
UNET WindReference=Eulerian
UNET WindDragFormulation=Hsu (1988)
UNET D2 Coriolis=0
UNET D2 Cores= 0
UNET D2 Theta= 1
UNET D2 Theta Warmup= 1
UNET D2 Z Tol= 0.01
UNET D2 Volume Tol= 0.01
UNET D2 Max Iterations= 20
UNET D2 Equation= 0
UNET D2 RampUpFraction=0.1
UNET D2 TimeSlices= 1
UNET D2 Turbulence Formulation=Non-Conservative (original)
UNET D2 Eddy Viscosity=0.3
UNET D2 Transverse Eddy Viscosity=0.1
UNET D2 Smagorinsky Mixing=0
UNET D2 BCVolumeCheck=0
UNET D2 Cores=0
UNET D2 SolverType=PARDISO (Direct)
UNET D2 Minimum Iterations= 3
UNET D2 Maximum Iterations= 30
UNET D2 Restart Number= 10
UNET D2 Relaxation Coeff=1.3
UNET D2 SOR Precondition Iterations= 10
UNET D2 ILUT Maximum Fill= 8
UNET D2 ILUT Tolerance=1E-08
UNET D2 Convergence Tolerance=0.00001
UNET D1D2 MaxIter= 0
UNET D1D2 ZTol=0.01
UNET D1D2 QTol=0.1
UNET D1D2 MinQTol=1
Write IC File= 0
Write IC File at Fixed DateTime=0
Write IC File at Sim End=0
Echo Input=False
Echo Parameters=False
Echo Output=False
Write Detailed= 0
HDF Write Warmup=0
HDF Write Time Slices=0
HDF Flush=0
HDF Compression= 1
HDF Chunk Size= 1
HDF Spatial Parts= 1
HDF Use Max Rows=0
HDF Fixed Rows= 1
Calibration Method= 0
Calibration Iterations= 20
Calibration Max Change=0.05
Calibration Tolerance=0.2
Calibration Maximum=1.5
Calibration Minimum=0.5
Calibration Optimization Method= 1
WQ AD Non Conservative
WQ ULTIMATE=-1
WQ Max Comp Step=1HOUR
WQ Output Interval=15MIN
WQ Output Selected Increments= 0
WQ Create Restart=0
WQ Fixed Restart=0
WQ System Summary=0
WQ Write To DSS=0
Sorting and Armoring Iterations= 10
XS Update Threshold= 0.02
Bed Roughness Predictor= 0
Hydraulics Update Threshold= 0.02
Energy Slope Method= 1
Volume Change Method= 1
Sediment Retention Method= 0
Sediment TS Multiplier= 1
Warm Up Method= 0
XS Weighting Method= 0
Number of US Weighted Cross Sections= 1
Number of DS Weighted Cross Sections= 1
Upstream XS Weight=0
Main XS Weight=1
Downstream XS Weight=0
Number of DS XS's Weighted with US Boundary= 1
Upstream Boundary Weight= 1
Weight of XSs Associated with US Boundary= 0
Number of US XS's Weighted with DS Boundary= 1
Downstream Boundary Weight= 0.5
Weight of XSs Associated with DS Boundary= 0.5
Percentile Method= 0
Sediment Output Level= 3
Mass or Volume Output= 0
Output Increment Type= 1
Profile and TS Output Increment= 1
Transport Output Increment 1
XS Output Flag= 0
XS Output Increment= 10
Read HDF5 Sediment Hotstart= 0
Sediment Hotstart Type= 0
Write Gradation File= 0
Read Gradation Hotstart= 0
Write HDF5 File= 1
Write Binary Output= 1
Write DSS Sediment File= 0
DSS Sediment Output Type= 1
SV Curve= 0
Specific Gage Flag= 0
Subcell Erosion Methods= 0
Subcell Deposition Methods= 0
Advection Scheme= 1
Matrix Solver= 0
Implicit Weighting Factor= 1
Maximum Outer Loop Convergence Iterations= 5
Convergence Maximum Absolute= 0.001
Convergence RMSE= 0.0001
Grain Fractions Max Abs Error= 0.001
Max Subgrid Regions= 1
Max Subgrid Length Scale= 3.402823E+38
Initial Layer Thickness= 3.402823E+38
Min Layer Thickness= 3.402823E+38
Max Layer Thickness= 3.402823E+38
Number of Layers= 5

--- SANDRNT1A.f01 (steady flow) ---

Flow Title=Flows
Program Version=6.31
Number of Profiles= 1
Profile Names=01pct
River Rch & RM=SANDRNT1A,Main            ,3258
     322
River Rch & RM=SANDRNT1A,Main            ,0
     322
Boundary for River Rch & Prof#=SANDRNT1A,Main            , 1
Up Type= 0
Dn Type= 1
Dn Known WS=1682.7
DSS Import GetInterval= 0
DSS Import GetPeak= 0
DSS Import FillOption= 0

--- SANDRNT1A.g01 (geometry) ---

Geom Title=Geometry
Program Version=6.31

River Reach=SANDRNT1A       ,Main
Reach XY= 30
2211776.14555457704961.7871917492211711.88805544704941.025838345
     2211632.155704870.9340000152211494.71000002704866.784000009
2211399.96100003704830.4420000022211336.80500002704770.748000011
2211246.37700003704788.0610000192211204.85500003704719.267000005
2211063.80499999704778.5310000182211008.43200001704771.177000016
2210938.34999999704741.7590000032210931.42500001704688.990999997
2210897.22900005704668.6439999942210784.33700001704698.062000006
     2210772.204704764.710000008     2210716.831704810.553000018
     2210654.962704783.3100000172210408.17500003704584.999000013
2210371.31700003704522.9300000072210333.48600003704349.800999999
2210101.49300003      704142.1032210026.20300004704027.350999996
2209966.30900003703999.4500000032209860.85700001703893.913000003
2209773.29099999703873.623999998     2209698.116703894.284999996
2209648.55200005      703943.4192209523.95699999      703977.816
      2209432.27704084.5840000062209320.86103376704079.219559908

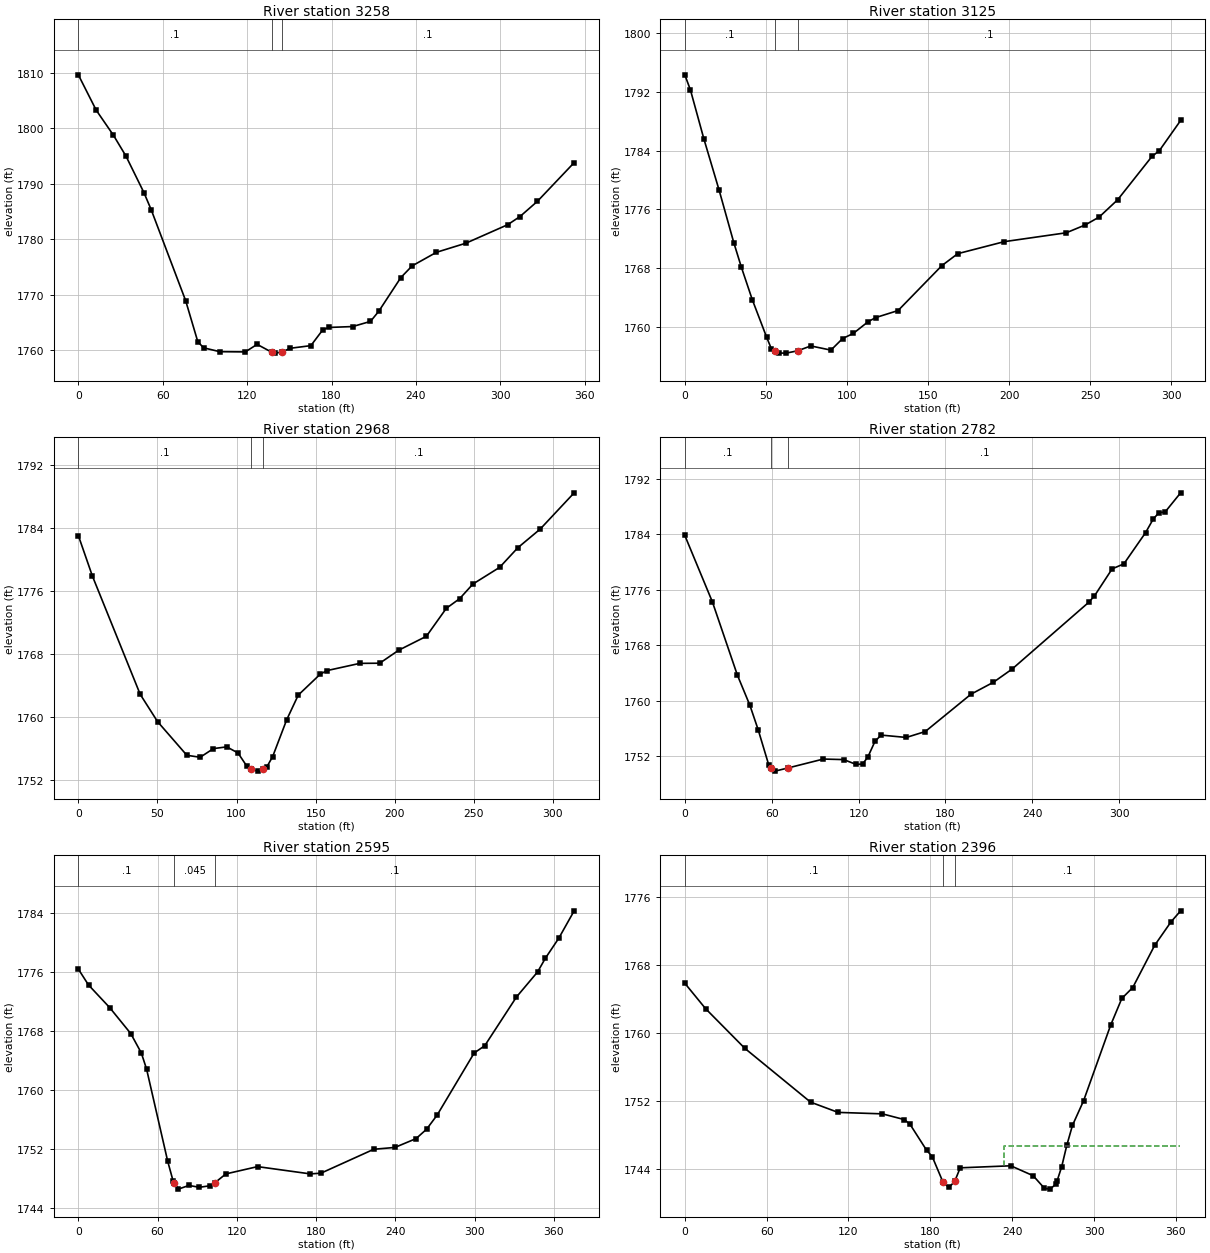
Type RM Length L Ch R = 1 ,3258    ,133.4,133.4,133.4
XS GIS Cut Line= 2
2211796.44022937704821.2036457262211679.79248919 705153.82294447
#Sta/Elev= 30
       0 1809.66    12.7 1803.29      25 1798.75    33.9 1794.99    46.6 1788.44
    51.8 1785.34    76.3 1768.94    84.9 1761.57      89 1760.44   100.6 1759.74
   118.7  1759.7   127.1 1761.06  137.371759.662   139.9 1759.48   144.5 1759.67
   150.8 1760.36   165.3 1760.83   173.8 1763.68     178 1764.11     195 1764.27
   207.7  1765.2   213.6 1767.03   229.3 1773.11   237.3 1775.21   254.6 1777.66
   275.5  1779.3   305.2 1782.63     314 1784.11   326.4 1786.86   352.5 1793.83
#Mann= 3 ,-1,0
       0      .1       0  137.37    .045       0   144.5      .1       0
Bank Sta=137.37,144.5
XS Rating Curve= 0 ,0
Exp/Cntr(USF)=0,0
Exp/Cntr=0.3,0.1

Type RM Length L Ch R = 1 ,3125    ,156.9,156.9,156.9
XS GIS Cut Line= 2
2211678.63756107704818.8937894852211527.34197727705084.527257232
#Sta/Elev= 30
       0 1794.34     3.5 1792.26    11.8 1785.57    21.1 1778.65    30.2 1771.45
    34.9 1768.08    41.6 1763.67    50.4 1758.57    53.3    1757   55.361756.684
    57.9 1756.38    62.5 1756.37    69.6 1756.69    77.7 1757.35    90.1 1756.78
    97.3 1758.36   103.9 1759.06   113.1 1760.67   117.7 1761.22   131.5 1762.18
   158.5 1768.31   168.3 1769.94     197 1771.58   235.2 1772.79   246.9 1773.86
   255.5 1774.94   266.9  1777.3     288  1783.2   292.6    1784   305.7 1788.11
#Mann= 3 ,-1,0
       0      .1       0   55.36    .045       0    69.6      .1       0
Bank Sta=55.36,69.6
XS Rating Curve= 0 ,0
Exp/Cntr(USF)=0,0
Exp/Cntr=0.3,0.1

Type RM Length L Ch R = 1 ,2968    ,164.4,185.9,164.4
XS GIS Cut Line= 2
2211526.18704915704759.9924553332211429.17308701705057.963910457
#Sta/Elev= 30
       0 1782.99     8.9 1777.84    39.1 1762.83    50.1 1759.36    68.6 1755.09
      77 1754.84    85.4 1755.94    93.8 1756.16   100.9 1755.39   106.4 1753.74
  109.31  1753.3   113.6 1753.08  116.991753.296     119 1753.57   122.8 1754.91
   131.7  1759.6     139 1762.73   152.7 1765.35   156.9 1765.83   177.9 1766.76
   190.5 1766.78   202.5 1768.43     220  1770.2   232.6 1773.75     241 1774.97
   249.4 1776.83   266.3 1778.95   277.8 1781.44   291.9  1783.8   313.4 1788.41
#Mann= 3 ,-1,0
       0      .1       0  109.31    .045       0  116.99      .1       0
Bank Sta=109.31,116.99
XS Rating Curve= 0 ,0
Exp/Cntr(USF)=0,0
Exp/Cntr=0.3,0.1

Type RM Length L Ch R = 1 ,2782    ,208.2,186.7,208.2
XS GIS Cut Line= 3
2211363.34063351 704711.534393862211305.21092195704853.847402263
2211337.54890933705039.790829684
#Sta/Elev= 30
       0 1783.81    19.1 1774.21    36.3  1763.7      45 1759.32    50.7 1755.81
    57.9 1750.81   59.62 1750.34    62.3 1749.86    71.61750.332    95.7  1751.6
   109.8 1751.52   118.4 1750.82   122.8 1750.89   126.4 1751.87   131.4 1754.16
   135.6 1755.05     153 1754.71   166.1 1755.56   197.7 1760.94   213.2 1762.66
   226.1 1764.56   278.9 1774.15     283  1775.1   295.2 1778.99   303.3 1779.71
   318.3 1784.21   323.6 1786.17   327.6  1787.1   331.7 1787.16   342.5 1789.94
#Mann= 3 ,0,0
       0      .1       0   59.62    .045       0    71.6      .1       0
Bank Sta=59.62,71.6
XS Rating Curve= 0 ,0
Exp/Cntr(USF)=0,0
Exp/Cntr=0.3,0.1

Type RM Length L Ch R = 1 ,2595    ,199.8,199.5,199.8
XS GIS Cut Line= 2
2211198.18746289  704629.48557772211198.18746289705004.837216908
#Sta/Elev= 30
       0 1776.44     7.7 1774.28    23.7 1771.21    39.7 1767.67    47.7 1765.03
    51.7 1762.82    67.7 1750.28    71.7 1747.66   72.641747.392    75.7 1746.52
    83.7 1747.02    91.7 1746.77    99.7 1746.98  103.411747.388   111.7 1748.59
   135.7 1749.58   175.7 1748.59   183.7 1748.69   223.7 1751.94   239.7 1752.19
   255.7 1753.39   263.7 1754.67   271.7  1756.6   299.7 1765.03   307.7 1766.02
   331.7 1772.64   347.7 1776.05   353.7 1777.94   363.7 1780.62   375.4 1784.36
#Mann= 3 ,-1,0
       0      .1       0   72.64    .045       0  103.41      .1       0
Bank Sta=72.64,103.41
XS Rating Curve= 0 ,0
Exp/Cntr(USF)=0,0
Exp/Cntr=0.3,0.1

Type RM Length L Ch R = 1 ,2396    ,252,252.3,252
XS GIS Cut Line= 4
2211051.51159156704582.1335247542211023.76740847704756.721823459
2210998.63326348704860.9069083652210991.45532929704940.161242152
#Sta/Elev= 30
       0 1765.83    15.2 1762.84      44 1758.16    92.2 1751.82   112.4 1750.61
   144.8 1750.44     161 1749.76   165.1 1749.21   177.2 1746.17   181.4  1745.4
   189.3 1742.39   193.7 1741.77   197.9 1742.49   201.9 1744.08     239 1744.32
   255.4 1743.15   263.7 1741.66   267.8 1741.57   271.9 1742.14     273 1742.57
   276.3 1744.21   280.1 1746.76   284.2 1749.08   292.3 1751.96   312.2 1760.89
   320.4 1764.04   328.4 1765.32   344.5  1770.3   356.4 1773.05   363.5 1774.36
#Mann= 3 ,-1,0
       0      .1       0   189.3    .045       0   197.9      .1       0
#XS Ineff= 1 ,-1
  233.66     363 1746.69
Permanent Ineff=
       F
Bank Sta=189.3,197.9
XS Rating Curve= 0 ,0
Exp/Cntr(USF)=0,0
Exp/Cntr=0.3,0.1

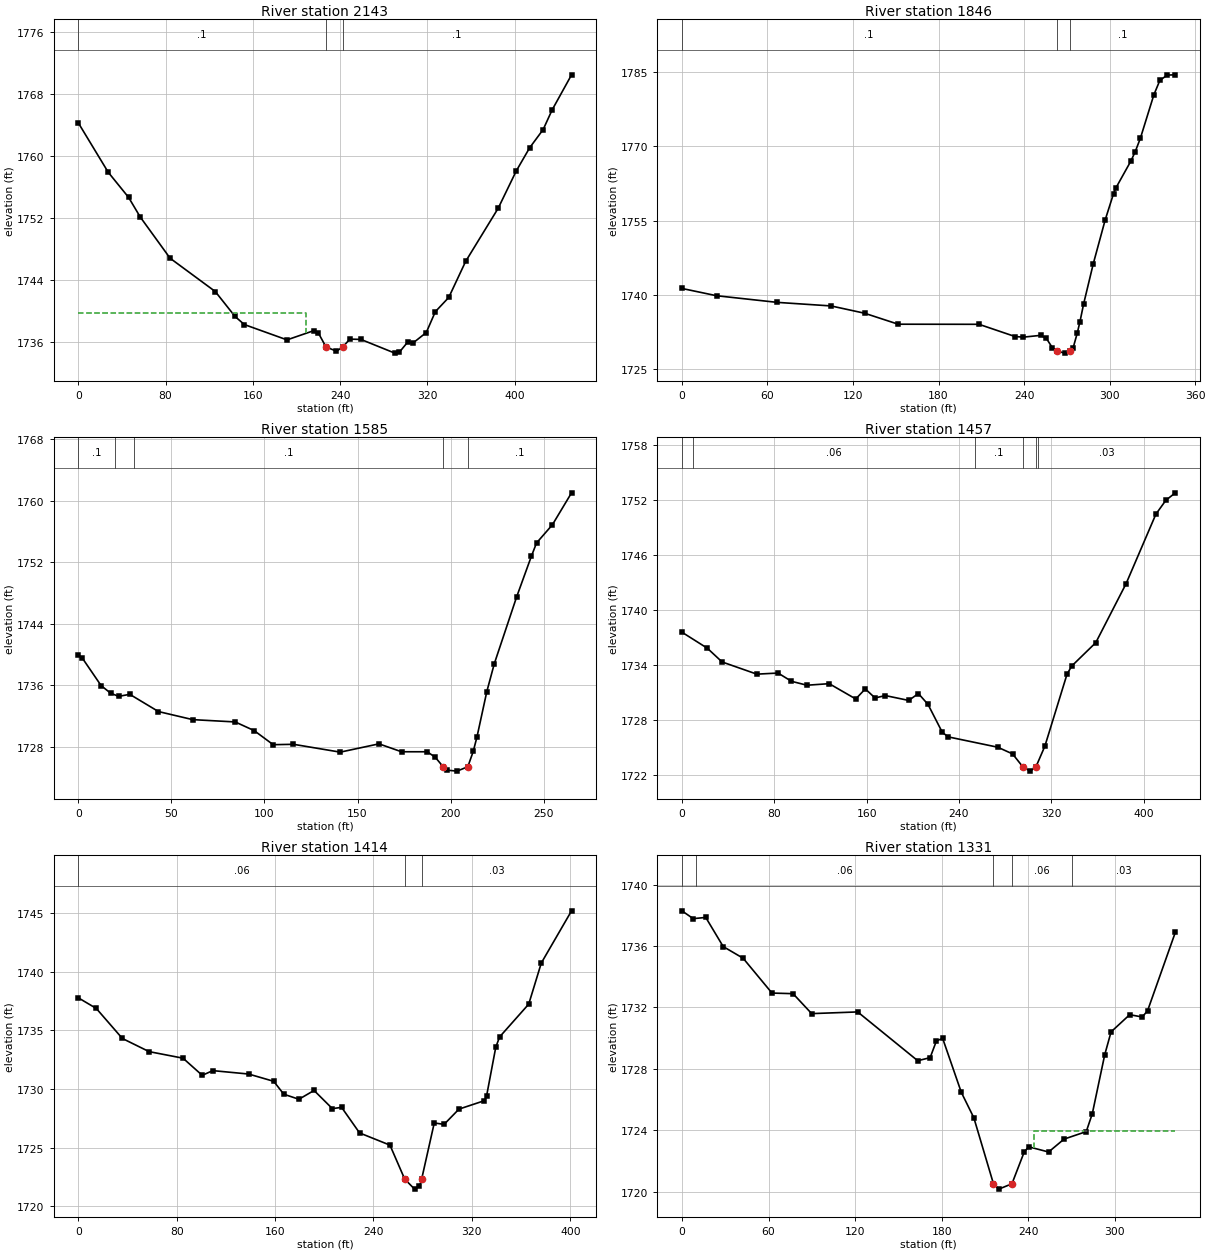
Type RM Length L Ch R = 1 ,2143    ,288.5,297.1,301.7
XS GIS Cut Line= 3
2210959.11734191704509.3730531542210820.52596744  704629.4855777
2210884.04701407704890.499332964
#Sta/Elev= 30
       0 1764.31    27.5 1757.91    46.2 1754.66    56.8 1752.14    84.2 1746.81
   125.6 1742.51   143.7 1739.29   152.2 1738.25   191.3 1736.27     216 1737.47
   220.1 1737.14     227 1735.36   236.6 1734.81  242.261735.339   248.9 1736.37
     259 1736.33   290.1 1734.56   294.2 1734.67     302 1736.01   306.6 1735.85
   318.9 1737.22   327.2 1739.91   339.5 1741.75     355 1746.41   384.8 1753.27
   401.3 1758.07   413.6 1761.07     426 1763.43   434.2 1765.96     452 1770.49
#Mann= 3 ,-1,0
       0      .1       0     227    .045       0  242.26      .1       0
#XS Ineff= 2 , 0
          208.47 1739.76
Permanent Ineff=
       F       F
Bank Sta=227,242.26
XS Rating Curve= 0 ,0
Exp/Cntr(USF)=0,0
Exp/Cntr=0.3,0.1

Type RM Length L Ch R = 1 ,1846    ,259.8,261.9,263.2
XS GIS Cut Line= 2
2210769.70913013704540.5561124112210586.07555895704833.907855053
#Sta/Elev= 30
       0 1741.31    24.3 1739.84    66.8  1738.5   104.6 1737.78   128.1 1736.31
   151.7 1734.09   208.4 1734.07   233.7  1731.6   239.6 1731.48   251.7 1731.84
   255.6 1731.25   259.9 1729.33   262.8 1728.68   268.6 1728.25  272.21 1728.69
   274.4 1729.27   277.3 1732.27   279.2 1734.56   281.8 1738.19   288.6 1746.34
   296.9 1755.13   302.8 1760.48   304.4 1761.59     315 1767.07   317.9 1768.87
   321.6 1771.63   331.1 1780.44   335.3 1783.34   340.5  1784.4   346.1 1784.45
#Mann= 3 ,-1,0
       0      .1       0   262.8    .045       0  272.21      .1       0
Bank Sta=262.8,272.21
XS Rating Curve= 0 ,0
Exp/Cntr(USF)=0,0
Exp/Cntr=0.3,0.1

Type RM Length L Ch R = 1 ,1585    ,117.3,127.1,137
XS GIS Cut Line= 3
2210581.76003205704472.2594881182210457.30702532704572.453742827
2210387.72867834704651.269231489
#Sta/Elev= 30
       0 1739.87       2 1739.59    12.3 1735.94    17.4 1734.95    21.7 1734.54
    27.7  1734.8    43.1 1732.56    61.5 1731.51    84.3 1731.21    94.5 1730.08
   104.7 1728.25   115.6  1728.3   140.7 1727.28   161.5 1728.36   173.6 1727.33
   187.4 1727.33   191.7 1726.62   196.11725.339   197.9 1724.94   203.4 1724.81
   209.2 1725.38   212.1 1727.37   214.1 1729.24   219.4 1735.16   223.4 1738.77
   235.4 1747.47   243.3 1752.75   246.1  1754.5   254.6 1756.86   264.9 1761.02
#Mann= 5 ,-1,0
       0      .1       0      20     .06       0      30      .1       0
   196.1    .045       0   209.2      .1       0
Bank Sta=196.1,209.2
XS Rating Curve= 0 ,0
Exp/Cntr(USF)=0,0
Exp/Cntr=0.3,0.1

Type RM Length L Ch R = 1 ,1457    ,43.3,43.4,43.5
XS GIS Cut Line= 6
2210568.66425778704317.8639362082210473.33859592 704354.85522248
 2210441.5195886704461.5271165212210401.28705965704498.978700068
2210318.13223496704494.3589875862210290.41396006704564.809602945
#Sta/Elev= 30
       0 1737.55      22  1735.8    34.8  1734.3    64.9 1732.97    83.3 1733.09
    94.9 1732.19   108.3 1731.76   127.6 1731.93   150.6 1730.26   158.9 1731.36
   167.3 1730.37   176.3 1730.63   196.5  1730.1   204.9 1730.85   213.2 1729.67
   225.6 1726.62   230.7 1726.12   273.7 1724.99   286.5 1724.26 295.578 1722.82
   301.7 1722.38 306.668 1722.82   314.5 1725.11   333.7 1732.97   337.8 1733.86
   358.6 1736.41   384.9 1742.86   410.7 1750.44   419.3 1751.95   427.5 1752.77
#Mann= 6 ,-1,0
       0      .1       0      10     .06       0  253.57      .1       0
 295.578    .045       0 306.668      .1       0  308.53     .03       0
Bank Sta=295.578,306.668
XS Rating Curve= 0 ,0
Exp/Cntr(USF)=0,0
Exp/Cntr=0.3,0.1

Type RM Length L Ch R = 1 ,1414    ,87.7,82.9,77.2
XS GIS Cut Line= 6
2210557.38851221704303.1841918472210437.55102071704352.469384133
2210421.29694923704427.7606653852210399.55466746704455.668895545
2210316.39984278704451.0491830622210288.68156788704521.499798421
#Sta/Elev= 30
       0 1737.78    14.7 1736.87    35.9 1734.31    57.6 1733.19    85.2 1732.63
   100.8 1731.17   109.4 1731.57   138.5 1731.28   158.9 1730.66   167.1 1729.56
   179.4 1729.13   191.7 1729.88   206.6 1728.33   214.1 1728.44   228.7 1726.26
   253.4 1725.22265.3642 1722.33   273.4 1721.47   277.4  1721.7279.17421722.332
   289.4 1727.11   297.4 1726.99   309.5 1728.29   330.2 1729.01   331.9 1729.39
   339.4 1733.56   342.5 1734.44   366.2 1737.24   376.4 1740.74     401 1745.19
#Mann= 3 ,-1,0
       0     .06       0265.3642    .045       0279.1742     .03       0
Bank Sta=265.3642,279.1742
XS Rating Curve= 0 ,0
Exp/Cntr(USF)=0,0
Exp/Cntr=0.3,0.1

Type RM Length L Ch R = 1 ,1331    ,164.9,160.1,153.9
XS GIS Cut Line= 2
2210551.42771533704291.0916383542210234.97741027704420.443587865
#Sta/Elev= 30
       0  1738.3     7.8 1737.79    16.5 1737.87    28.6 1735.97    42.4 1735.21
    62.4 1732.94      77  1732.9    89.9  1731.6   121.8 1731.71   163.4 1728.53
     172 1728.73   176.4 1729.83   180.7 1729.98   193.6 1726.47   202.3 1724.81
  215.891720.507   219.6 1720.16   228.7 1720.51   237.2 1722.58   240.3 1722.92
   254.1 1722.58   264.8 1723.42   280.2 1723.91   284.4 1725.08     293 1728.92
   297.4 1730.41   310.3 1731.53     319 1731.38   322.7 1731.79   341.9 1736.89
#Mann= 5 ,-1,0
       0     .05       0      10     .06       0  215.89    .045       0
   228.7     .06       0     270     .03       0
#XS Ineff= 2 , 0
                          243.73         1723.97
Permanent Ineff=
       F       F
Bank Sta=215.89,228.7
XS Rating Curve= 0 ,0
Exp/Cntr(USF)=0,0
Exp/Cntr=0.3,0.1

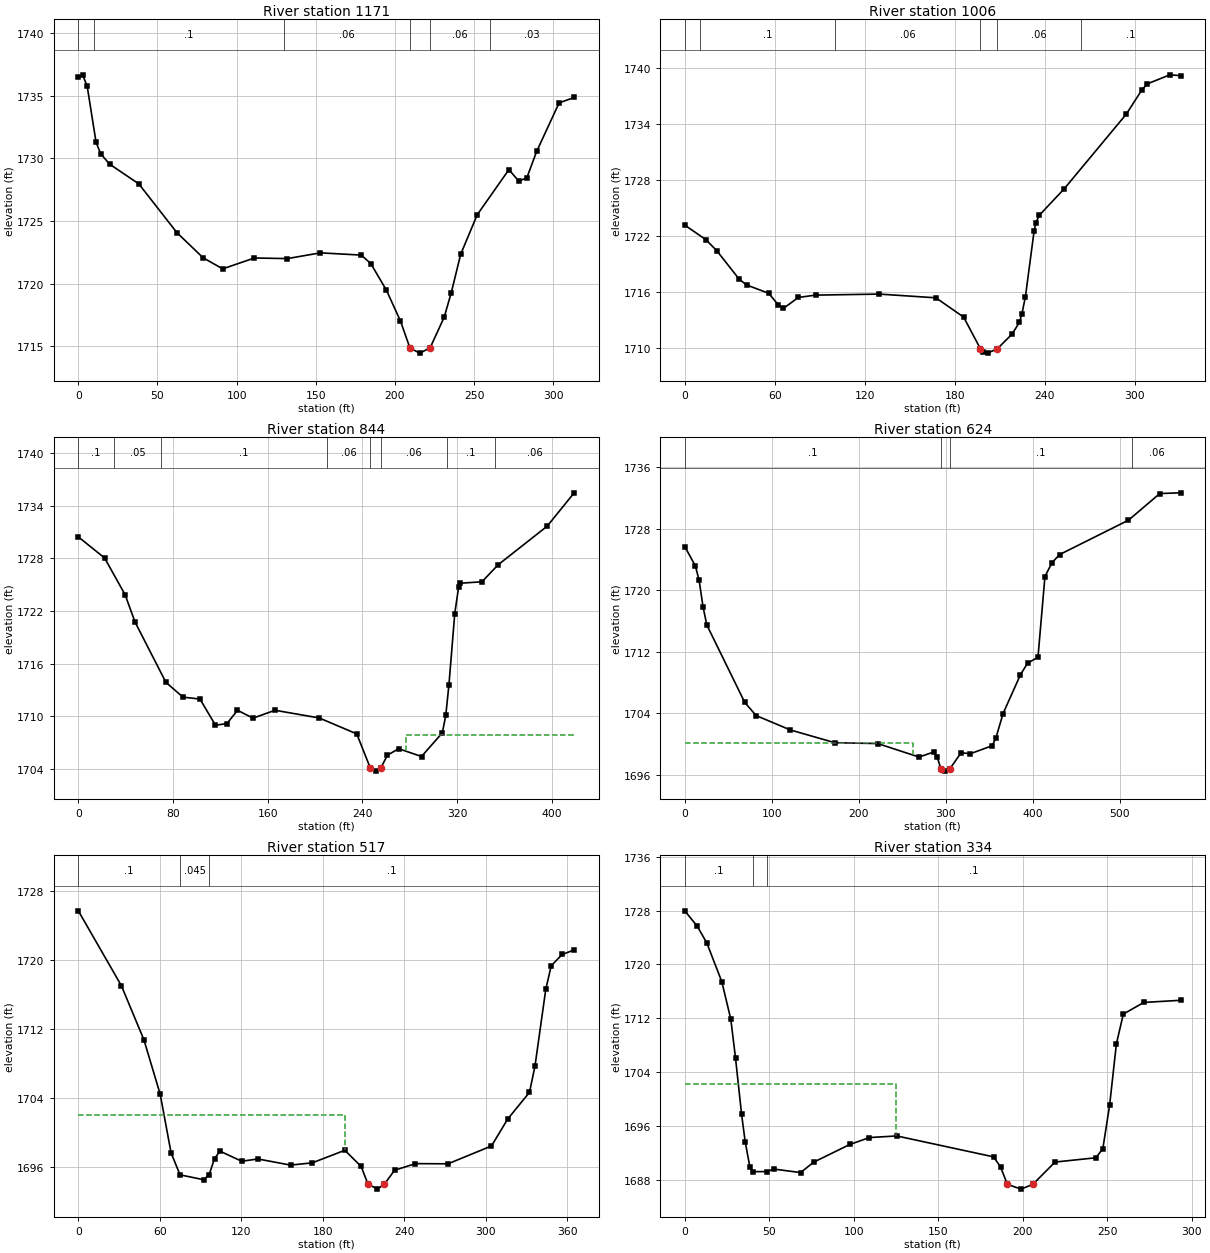
Type RM Length L Ch R = 1 ,1171    ,162.3,165.2,167.7
XS GIS Cut Line= 2
2210374.72371287704095.9087859662210173.76621988704336.133835059
#Sta/Elev= 30
       0 1736.47     2.7 1736.67     5.6 1735.76    11.2 1731.28    14.1 1730.37
    19.7 1729.54    38.2 1727.96    62.3 1724.06    78.8 1722.06    91.2 1721.17
   111.2 1722.04     132 1721.99   152.9 1722.45   178.8 1722.27   184.8 1721.58
   194.6 1719.47   203.5    1717  209.471714.846   215.7 1714.44   222.2 1714.86
   231.1 1717.31   235.6 1719.28   241.5 1722.33     252  1725.5     272  1729.1
   278.2 1728.18   283.3 1728.44   289.5 1730.55   303.7 1734.43   313.2 1734.86
#Mann= 6 ,-1,0
       0     .06       0      10      .1       0     130     .06       0
  209.47    .045       0   222.2     .06       0     260     .03       0
Bank Sta=209.47,222.2
XS Rating Curve= 0 ,0
Exp/Cntr(USF)=0,0
Exp/Cntr=0.3,0.1

Type RM Length L Ch R = 1 ,1006    ,161.7,162.3,162.5
XS GIS Cut Line= 3
2210277.70975074704037.0074518142210087.14661083704173.288970049
2210036.32977352704255.288866614
#Sta/Elev= 30
       0 1723.13      14 1721.58    21.3  1720.4    36.3 1717.34    41.2 1716.73
      56 1715.83    62.2 1714.62    65.8 1714.22    75.7 1715.39    87.2 1715.64
   129.7 1715.75   167.5 1715.35     186 1713.28   197.21709.886   199.1 1709.51
   201.9 1709.43   208.4 1709.89   218.3 1711.47   223.2 1712.73   224.9 1713.67
   227.2 1715.49     233 1722.53   234.1 1723.37   236.4 1724.18     253 1727.01
   294.5 1735.02   304.7 1737.57   308.3 1738.24   323.5 1739.22   330.7 1739.13
#Mann= 6 ,-1,0
       0     .05       0      10      .1       0     100     .06       0
   197.2    .045       0   208.4     .06       0  264.28      .1       0
Bank Sta=197.2,208.4
XS Rating Curve= 0 ,0
Exp/Cntr(USF)=0,0
Exp/Cntr=0.3,0.1

Type RM Length L Ch R = 1 ,844     ,225.6,219.1,212.4
XS GIS Cut Line= 3
2210228.04784155703882.2470836482209986.66786434704046.246876779
2209924.30174582 704157.11997636
#Sta/Elev= 30
       0 1730.46    22.2 1728.05    39.5 1723.86    47.9 1720.74      74 1713.85
    88.4 1712.16   102.8 1711.94   115.9 1708.95   125.6 1709.14   134.5 1710.66
   147.6 1709.76   166.2 1710.66   203.6 1709.78   235.3 1707.96   246.8 1704.04
   251.3 1703.71  255.491704.041   261.2 1705.53   270.7 1706.27     290 1705.38
   307.6 1708.08   310.5 1710.07   313.2  1713.6   318.1  1721.7   321.4 1724.77
   322.7 1725.17   341.1 1725.33   354.8 1727.28   396.2 1731.68     419 1735.49
#Mann= 8 ,-1,0
       0      .1       0      30     .05       0      70      .1       0
     210     .06       0   246.8    .045       0  255.49     .06       0
  311.82      .1       0  351.82     .06       0
#XS Ineff= 2 , 0
                          276.49         1707.89
Permanent Ineff=
       F       F
Bank Sta=246.8,255.49
XS Rating Curve= 0 ,0
Exp/Cntr(USF)=0,0
Exp/Cntr=0.3,0.1

Type RM Length L Ch R = 1 ,624     ,110.7,107.2,104
XS GIS Cut Line= 4
2210103.31560452703749.4303497752209863.09055543703854.528808753
2209831.90749617703951.5427708872209835.37228053 704157.11997636
#Sta/Elev= 30
       0 1725.67    12.2 1723.14    16.5 1721.26    20.9 1717.86    25.3 1715.47
    68.9 1705.38      82 1703.67   121.3  1701.8   172.3 1700.14   221.7 1700.03
   269.2 1698.27     286 1698.93   290.2 1698.22  294.191696.739   298.4 1696.44
   304.8 1696.78   317.5 1698.84     328  1698.7   353.2 1699.75   357.4 1700.74
   365.7 1703.94   385.7    1709   393.8 1710.49   405.8 1711.27   413.8 1721.77
   421.8 1723.56   430.6 1724.63   509.8 1729.11   545.8 1732.58   569.7 1732.67
#Mann= 4 ,-1,0
       0      .1       0  294.19    .045       0   304.8      .1       0
  514.11     .06       0
#XS Ineff= 2 , 0
          262.58 1700.04
Permanent Ineff=
       F       F
Bank Sta=294.19,304.8
XS Rating Curve= 0 ,0
Exp/Cntr(USF)=0,0
Exp/Cntr=0.3,0.1

Type RM Length L Ch R = 1 ,517     ,185,183.6,183.8
XS GIS Cut Line= 2
2209742.91286004703656.9082826342209750.29733044704022.029319073
#Sta/Elev= 30
       0 1725.72    31.7 1717.03    48.3 1710.75    60.3 1704.42    68.3 1697.63
    74.9 1695.07    92.3  1694.5    96.3 1695.07   100.3 1696.95   104.3 1697.82
   120.3 1696.65   132.3 1696.91   156.3  1696.2   172.3 1696.46   196.3 1697.92
   208.3 1696.04   213.3 1694.01   220.3 1693.41  225.45 1693.99   232.9  1695.6
   248.3 1696.37   272.3 1696.35   304.3 1698.42   316.3 1701.56   332.3 1704.65
   336.3 1707.65   344.3 1716.61   348.3 1719.34   356.3 1720.65   365.2 1721.18
#Mann= 3 ,-1,0
       0      .1       0    74.9    .045       0    96.3      .1       0
#XS Ineff= 2 , 0
          196.28 1702.01
Permanent Ineff=
       F       F
Bank Sta=213.3,225.45
XS Rating Curve= 0 ,0
Exp/Cntr=0.3,0.1

Type RM Length L Ch R = 1 ,334     ,325.9,333.7,329.7
XS GIS Cut Line= 3
 2209488.8266259703794.1115650842209579.90176083703880.263719749
2209601.23467532704046.824552102
#Sta/Elev= 30
       0 1727.96     7.4 1725.66      13  1723.2    21.9 1717.43    27.2 1711.87
      30  1706.1    33.6 1697.72    35.7 1693.69    38.5  1689.9   40.09 1689.21
    48.7 1689.23    52.6  1689.6    68.5 1689.08    76.2 1690.62    97.6 1693.25
   109.2 1694.28   125.4 1694.52   182.7 1691.41   186.8  1689.9   190.8 1687.34
   198.9 1686.62   205.9 1687.33     219 1690.64   243.2 1691.28   247.3 1692.65
   251.3 1699.09   255.3 1708.19   259.4 1712.62   271.5 1714.35   293.3 1714.67
#Mann= 3 ,-1,0
       0      .1       0   40.09    .045       0    48.7      .1       0
#XS Ineff= 2 , 0
          125.07  1702.3
Permanent Ineff=
       F       F
Bank Sta=190.8,205.9
XS Rating Curve= 0 ,0
Exp/Cntr=0.3,0.1

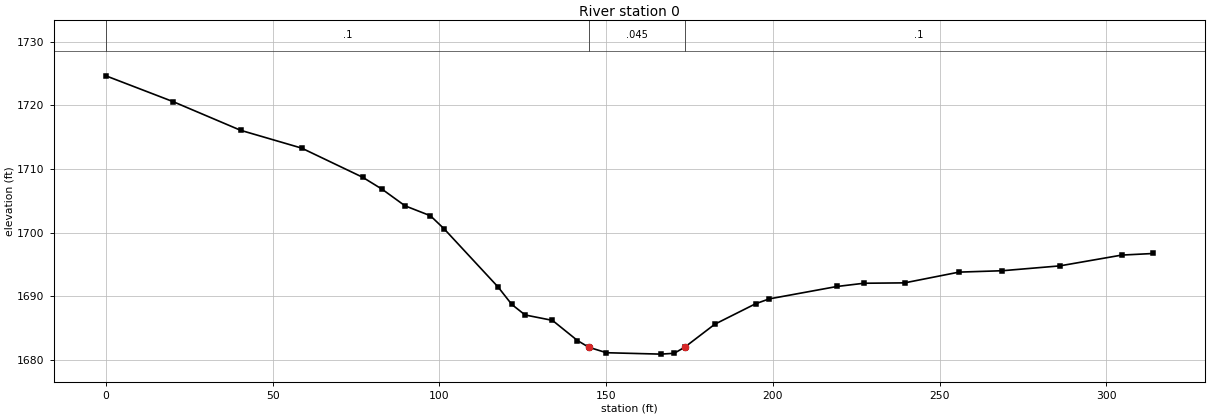
Type RM Length L Ch R = 1 ,0       ,213.2,198.3,188
XS GIS Cut Line= 2
2209291.76560099703917.4291818852209347.37704474704226.482943066
#Sta/Elev= 30
       0 1724.66    20.1 1720.61    40.4 1716.09    58.7 1713.29      77  1708.7
    82.8 1706.83    89.7 1704.21    97.3 1702.65   101.4  1700.6   117.6 1691.44
   121.7  1688.7   125.7 1687.04   133.9 1686.19   141.4 1683.02   144.8 1681.96
   150.1  1681.1   166.4 1680.88   170.4 1681.01  173.54 1681.96   182.6 1685.59
   194.8  1688.8   198.9 1689.57   219.2 1691.52   227.3 1692.03   239.5 1692.09
   255.8 1693.78   268.8    1694     286 1694.76   304.6 1696.46     314 1696.71
#Mann= 3 ,-1,0
       0      .1       0   144.8    .045       0  173.54      .1       0
Bank Sta=144.8,173.54
XS Rating Curve= 0 ,0
Exp/Cntr=0.3,0.1
LCMann Table=0

Chan Stop Cuts=-1
Use User Specified Reach Order=0
Composite Channel Slope=5